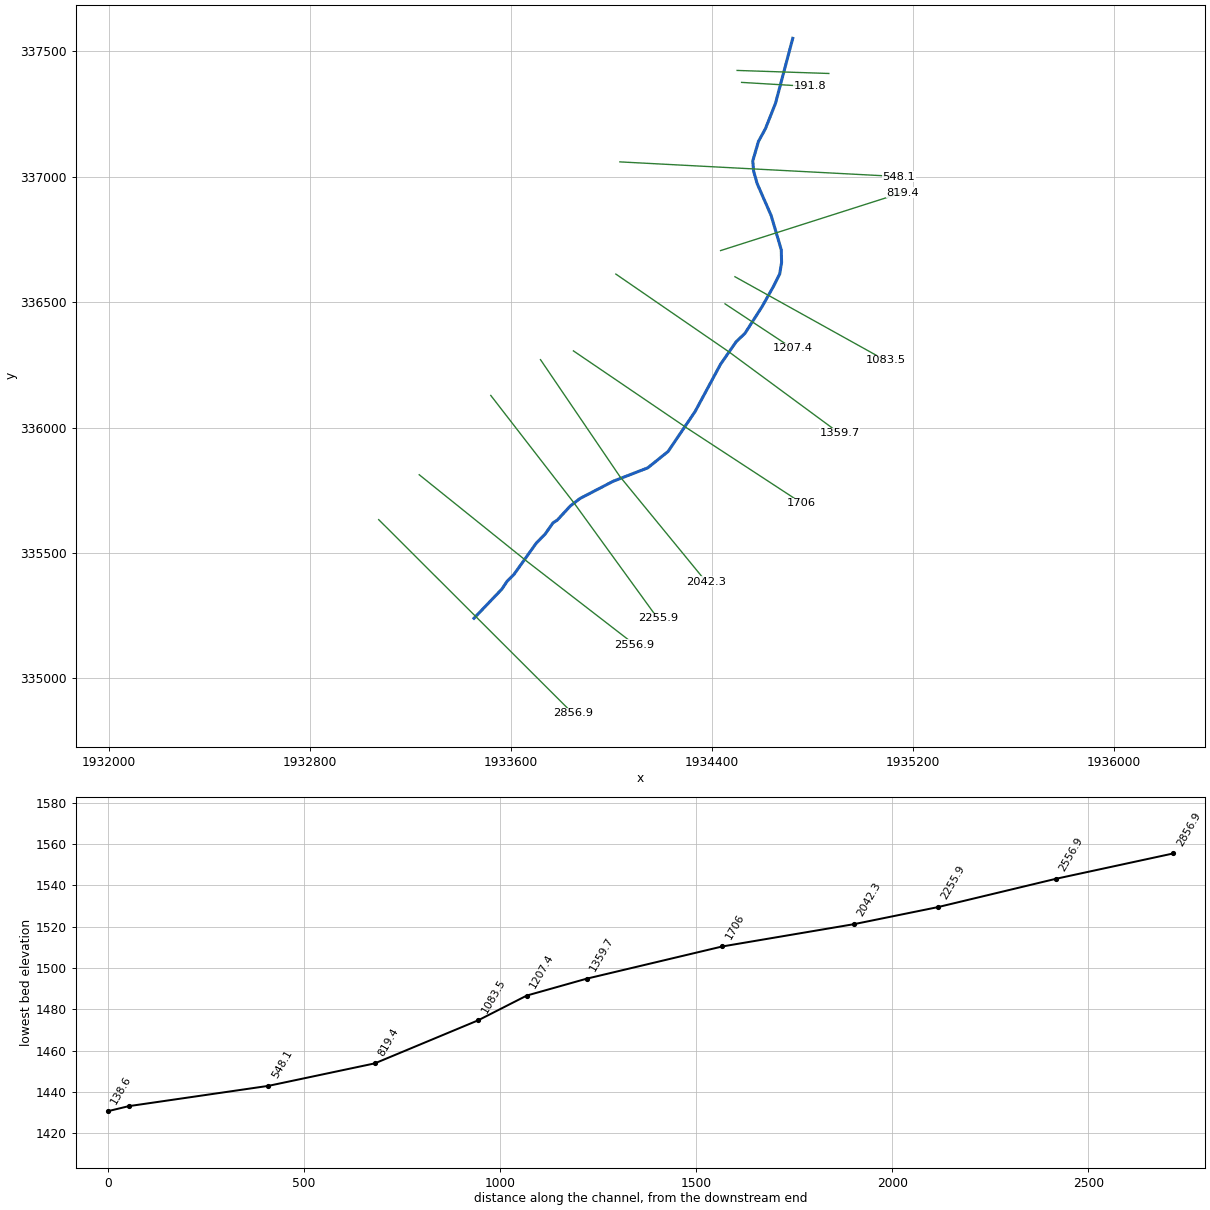
--- BarrenBrch.prj (project) ---

Proj Title=BarrenBrch
Current Plan=p01
Geom File=g01
Flow File=f01
Plan File=p01
DSS Export Rating Curves=0
DSS Export Rating Curve Sorted=0
DSS Export Volume Flow Curves=0
DXF OffsetX=0
DXF OffsetY=0
DXF ScaleX=0
DXF ScaleY=0

--- BarrenBrch.p01 (plan) ---

Plan Title=Floodplain
Program Version=4.00
Geom File=g01
Flow File=f01
K Sum by GR=0
Std Step Tol=0.01
Critical Tol=0.01
Num of Std Step Trials=20
Max Error Tol=0.3
Flow Tol Ratio=0.001
Split Flow NTrial=30
Split Flow Tol=0.02
Split Flow Ratio=0.02
Log Output Level=0
Friction Slope Method=1
Unsteady Friction Slope Method=2
Unsteady Bridges Friction Slope Method=1
Global Log Level=0
CheckData=False
Run HTab=0
Run UNet=0
Run PostProcess=0
UNET Theta=0
UNET Theta Warmup=0
UNET ZTol=0
UNET ZSATol=0
UNET MxIter=0
UNET MaxInSteps=0
UNET DtIC=0
UNET DtMin=0
UNET MaxCRTS=0
UNET WFStab=0
UNET SFStab=0
UNET WFX=0
UNET SFX=0
UNET DSS MLevel=0
UNET DZMax Abort=0
UNET Convert EG Bridges=0
UNET Use Existing IB Tables=0
UNET Froude Limit=0
UNET Froude Power=0
Write IC File=0
Echo Input=False
Echo Output=False
Write Detailed=0

--- BarrenBrch.f01 (steady flow) ---

Flow Title=NFF Regression Equation
Program Version=4.00
Number of Profiles=1
Profile Names=P100yr
River Rch & RM=BarrenBrch,Main      ,2856.9
441.3681
River Rch & RM=BarrenBrch,Main      ,2556.9
702.7223
River Rch & RM=BarrenBrch,Main      ,1083.5
727.5757
River Rch & RM=BarrenBrch,Main      ,819.4
1341.043
River Rch & RM=BarrenBrch,Main      ,191.8
1344.221
Boundary for River Rch & Prof#=BarrenBrch,Main      ,1
Up Type=0
Dn Type=3
Dn Slope=0.039665

--- BarrenBrch.g01 (geometry) ---

Geom Title=USGS 3m DEM
Program Version=4.00

River Reach=BarrenBrch     ,Main
Reach XY= 30
     1933454.115      335239.760     1933565.226      335356.080
     1933586.059      335387.330     1933613.127      335414.397
     1933701.441      335538.534     1933737.752      335575.946
     1933768.561      335619.959     1933785.670      335631.187
     1933837.795      335687.677     1933875.989      335717.191
     1934008.436      335786.111     1934145.552      335839.283
     1934226.684      335904.691     1934334.323      336064.413
     1934435.017      336251.913     1934497.517      336342.191
     1934532.239      336375.177     1934599.948      336481.080
     1934646.823      336564.413     1934670.718      336612.304
     1934678.073      336657.980     1934676.902      336708.349
     1934636.406      336845.663     1934580.851      336972.399
     1934566.962      337021.010     1934563.489      337062.677
     1934585.941      337140.008     1934613.837      337191.149
     1934653.767      337291.844     1934722.564      337551.260

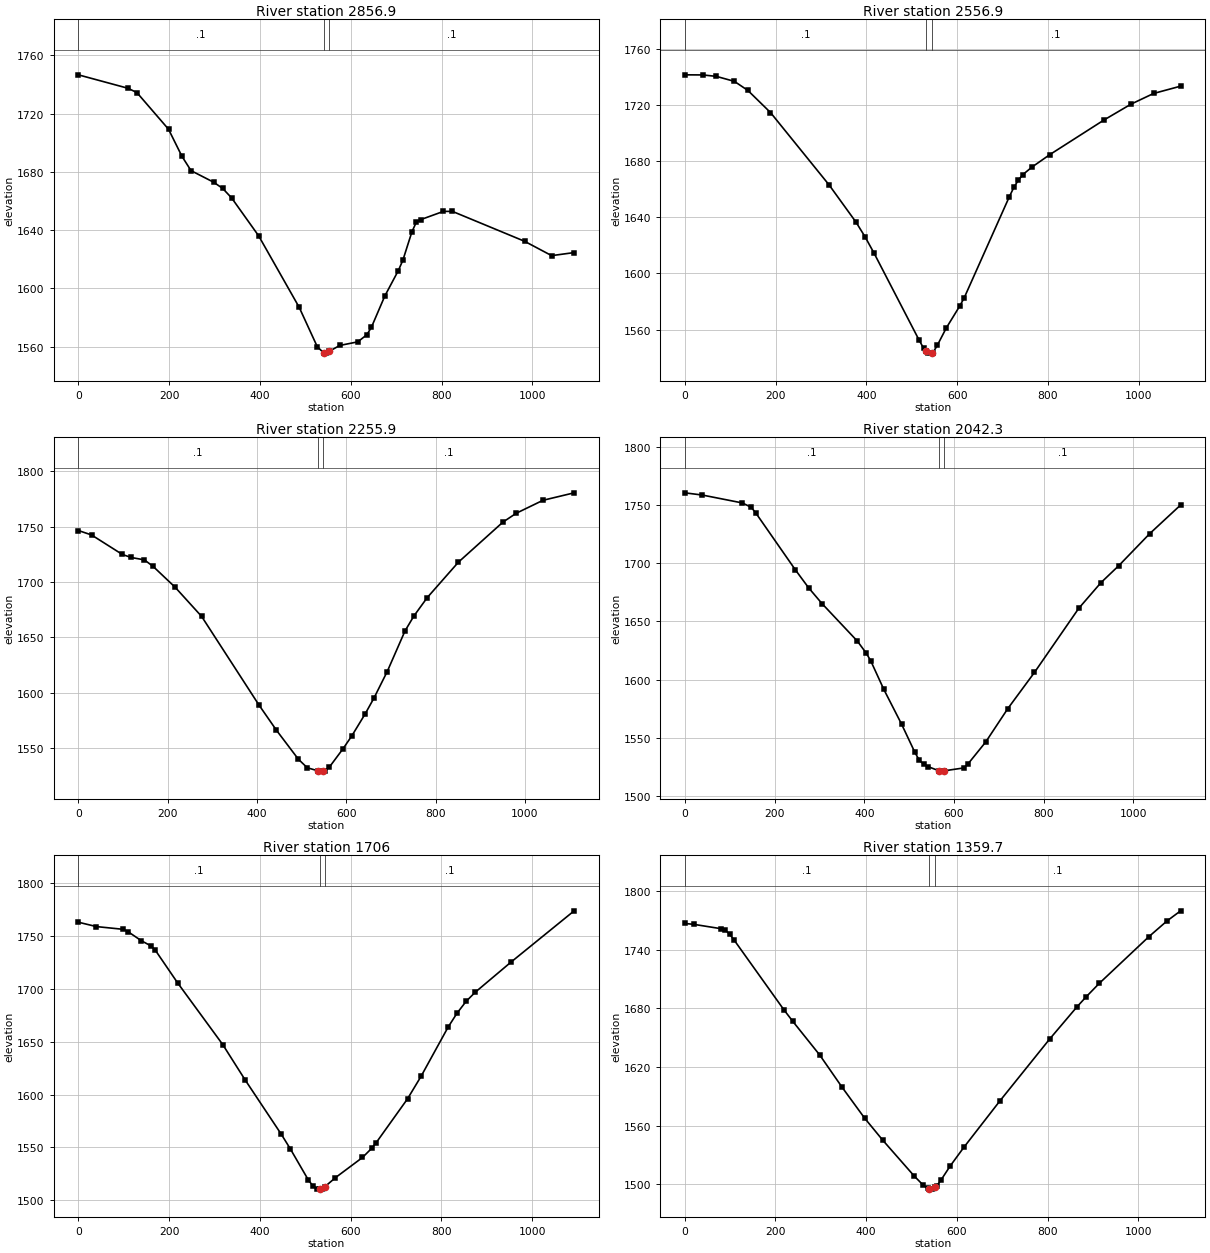
Type RM Length L Ch R = 1 ,2856.9,297.6,299.8,302.3
XS GIS Cut Line= 3
     1933075.104      335632.910     1933461.186      335246.831
     1933847.268      334860.753
#Sta/Elev= 30
       0 1746.62   109.2 1737.40   129.0 1734.42   198.6 1709.26   228.3 1690.58
   248.2 1680.81   297.8 1672.88   317.7 1668.65   337.5 1662.11   397.1 1636.03
   486.4 1586.92   526.2 1559.89     540 1555.70   546.0 1555.45     552 1556.60
   575.8 1560.72   615.5 1563.20   635.4 1568.08   645.3 1573.07   675.0 1594.69
   704.8 1612.19   714.8 1619.30   734.6 1638.72   744.6 1645.57   754.5 1647.21
   804.1 1652.82   824.0 1652.80   982.8 1632.28  1042.4 1622.42  1092.0 1624.52
#Mann= 3 , 0 , 0
       0     0.1       0     540   0.045       0     552     0.1       0
Bank Sta=     540,     552
Exp/Cntr=0.3,0.1

Type RM Length L Ch R = 1 ,2556.9,305.8,300.8,294.9
XS GIS Cut Line= 3
     1933236.382      335811.834     1933661.670      335469.225
     1934093.389      335134.992
#Sta/Elev= 30
       0 1741.66    39.7 1741.58    69.5 1740.56   109.2 1737.00   139.0 1730.51
   188.7 1714.78   317.7 1663.18   377.3 1636.49   397.2 1626.03   417.0 1614.38
   516.3 1552.30   526.3 1546.49     532 1544.57   536.2 1543.16     544 1543.25
   546.1 1543.28   556.0 1548.61   575.9 1561.07   605.7 1576.80   615.6 1582.75
   714.9 1654.78   724.8 1661.39   734.7 1666.56   744.7 1670.53   764.5 1675.82
   804.2 1684.80   923.4 1709.46   982.9 1720.76  1032.5 1728.36  1092.1 1733.58
#Mann= 3 , 0 , 0
       0     0.1       0     532   0.045       0     544     0.1       0
Bank Sta=     532,     544
Exp/Cntr=0.3,0.1

Type RM Length L Ch R = 1 ,2255.9,213.6,213.4,215
XS GIS Cut Line= 3
     1933521.018      336128.021     1933852.503      335699.042
     1934185.534      335239.006
#Sta/Elev= 30
       0 1746.50    29.6 1742.48    98.6 1724.88   118.3 1722.16   147.8 1720.02
   167.6 1714.06   216.8 1695.29   276.0 1669.02   404.1 1589.29   443.6 1566.32
   492.8 1540.13   512.6 1532.51   536.1 1529.79   542.1 1529.47   548.1 1529.79
   552.1 1530.01   562.1 1533.14   592.0 1549.30   611.9 1561.01   641.8 1580.83
   661.7 1595.22   691.6 1619.31   731.4 1655.93   751.4 1669.45   781.3 1686.05
   851.0 1717.96   950.6 1754.06   980.5 1762.07  1040.3 1773.74  1110.1 1780.48
#Mann= 3 , 0 , 0
       0     0.1       0   536.1   0.045       0   548.1     0.1       0
Bank Sta=   536.1,   548.1
Exp/Cntr=0.3,0.1

Type RM Length L Ch R = 1 ,2042.3,329.4,336.2,342.2
XS GIS Cut Line= 3
     1933718.833      336270.603     1934034.280      335805.410
     1934378.233      335385.022
#Sta/Elev= 30
       0 1760.69    39.4 1758.76   128.2 1751.99   147.9 1748.28   157.8 1743.61
   246.5 1694.40   276.1 1678.92   305.7 1665.44   384.6 1633.12   404.3 1622.83
   414.2 1616.35   443.7 1591.48   483.2 1561.67   512.8 1537.41   522.6 1530.65
   532.5 1527.13   542.3 1525.08   566.7 1521.54   571.9 1521.24   578.7 1521.54
   621.3 1523.96   631.2 1527.42   670.7 1546.29   720.1 1575.10   779.3 1606.11
   878.1 1661.30   927.5 1683.36   967.0 1697.89  1036.1 1725.49  1105.2 1750.22
#Mann= 3 , 0 , 0
       0     0.1       0   566.7   0.045       0   578.7     0.1       0
Bank Sta=   566.7,   578.7
Exp/Cntr=0.3,0.1

Type RM Length L Ch R = 1 ,1706,346.4,346.2,345.2
XS GIS Cut Line= 3
     1933849.878      336305.501     1934301.877      335997.748
     1934758.462      335698.604
#Sta/Elev= 30
       0 1763.22    39.8 1759.08    99.4 1756.46   109.4 1754.27   139.2 1745.61
   159.1 1741.00   169.0 1737.12   218.7 1705.83   318.2 1647.37   367.9 1613.67
   447.4 1562.32   467.3 1548.49   507.0 1519.04   517.0 1513.46   526.9 1510.44
   531.8 1510.63   536.9 1510.83   543.8 1512.91   566.7 1521.32   626.2 1540.40
   646.1 1548.92   656.0 1554.18   725.5 1595.97   755.2 1617.19   814.8 1663.78
   834.6 1677.09   854.5 1688.21   874.3 1696.76   953.7 1725.50  1092.7 1774.00
#Mann= 3 , 0 , 0
       0     0.1       0   531.8   0.045       0   543.8     0.1       0
Bank Sta=   531.8,   543.8
Exp/Cntr=0.3,0.1

Type RM Length L Ch R = 1 ,1359.7,151.9,152.3,153.4
XS GIS Cut Line= 3
     1934018.650      336611.683     1934467.921      336302.135
     1934908.842      335976.738
#Sta/Elev= 30
       0 1767.12    19.8 1766.21    79.4 1761.79    89.3 1760.41    99.2 1755.97
   109.1 1749.91   218.2 1678.87   238.1 1666.84   297.6 1632.28   347.2 1599.06
   396.8 1567.47   436.5 1545.04   505.9 1508.30   525.8 1498.92   535.7 1495.65
   539.6 1495.33   545.6 1494.83   551.6 1496.72   555.6 1497.98   565.5 1504.43
   585.4 1518.58   615.3 1537.56   695.0 1585.25   804.6 1648.57   864.4 1681.34
   884.3 1691.47   914.2 1705.74  1023.8 1753.67  1063.7 1769.74  1093.6 1780.06
#Mann= 3 , 0 , 0
       0     0.1       0   539.6   0.045       0   551.6     0.1       0
Bank Sta=   539.6,   551.6
Exp/Cntr=0.3,0.1

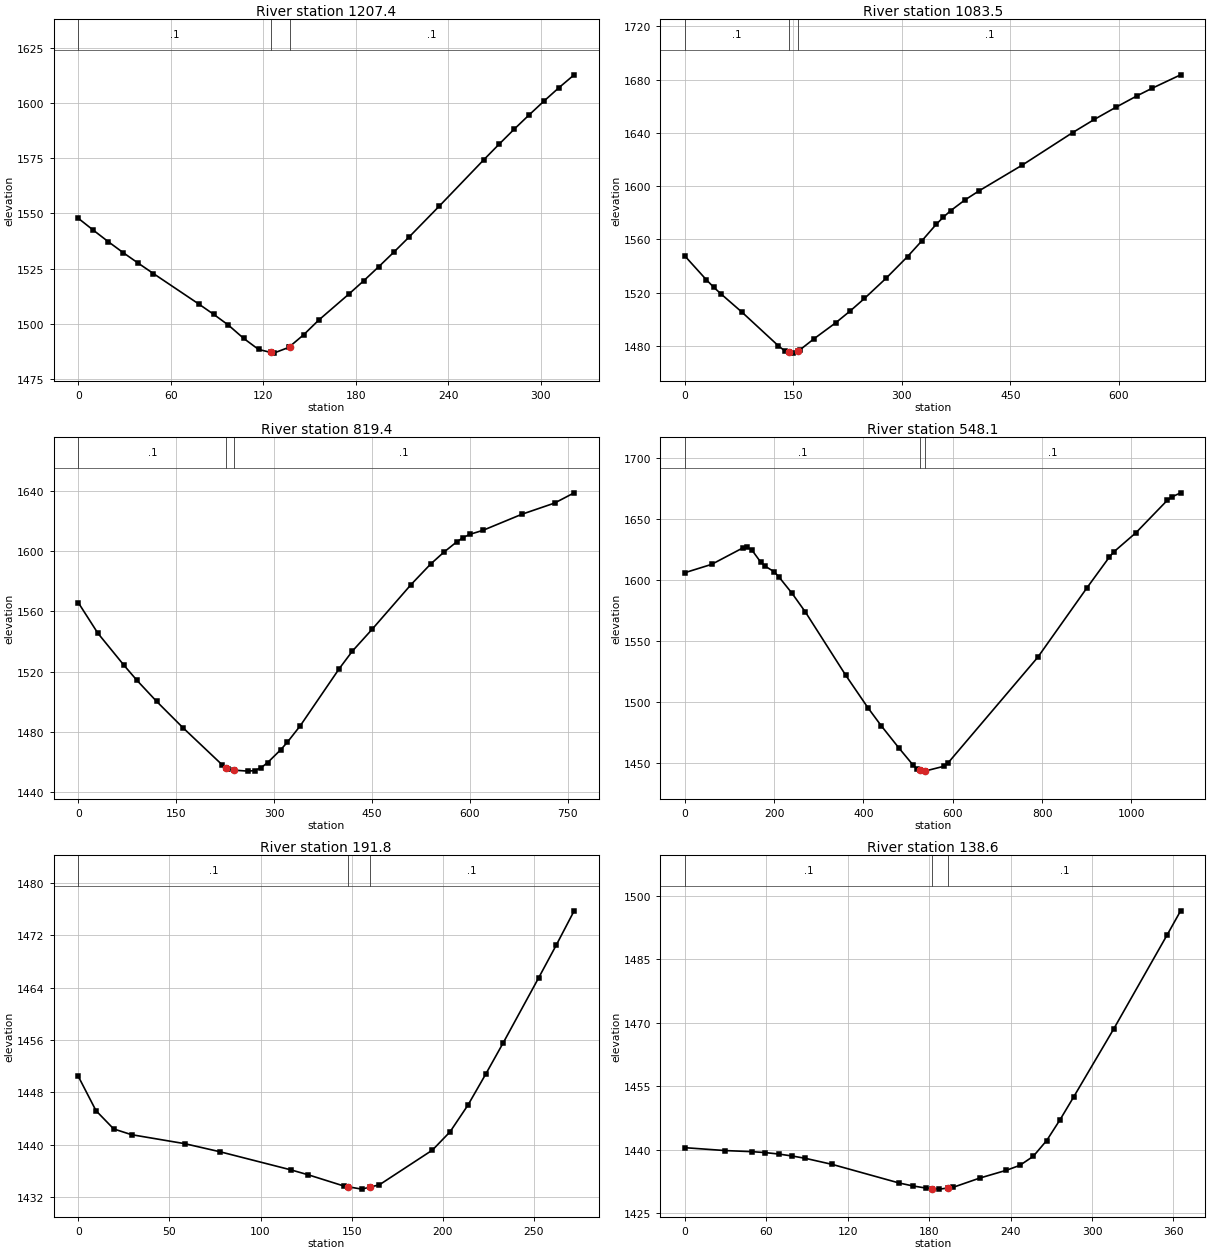
Type RM Length L Ch R = 1 ,1207.4,122.2,123.8,125.4
XS GIS Cut Line= 2
     1934452.973      336493.080     1934721.181      336315.650
#Sta/Elev= 30
       0 1547.76     9.8 1542.35    19.5 1537.14    29.2 1532.16    39.0 1527.37
    48.7 1522.74    78.0 1509.00    87.7 1504.31    97.4 1499.35   107.2 1493.39
   116.9 1488.36     125 1486.98   126.7 1486.69   136.4 1489.26     137 1489.61
   146.2 1495.04   155.9 1501.64   175.4 1513.40   185.2 1519.53   194.9 1525.88
   204.6 1532.41   214.4 1539.20   233.9 1553.14   263.1 1574.38   272.9 1581.34
   282.6 1588.08   292.4 1594.63   302.1 1600.93   311.8 1607.00   321.6 1612.78
#Mann= 3 , 0 , 0
       0     0.1       0     125   0.045       0     137     0.1       0
Bank Sta=     125,     137
Exp/Cntr=0.3,0.1

Type RM Length L Ch R = 1 ,1083.5,246.5,263.8,281.1
XS GIS Cut Line= 2
     1934492.586      336601.097     1935091.127      336267.828
#Sta/Elev= 30
       0 1547.67    29.8 1529.76    39.7 1524.32    49.6 1519.36    79.4 1505.27
   129.1 1480.32   139.0 1476.02   144.6 1475.29   148.9 1474.73   156.6 1476.57
   158.9 1477.12   178.7 1485.56   208.5 1497.49   228.4 1506.31   248.2 1515.73
   278.0 1530.86   307.8 1547.20   327.6 1559.03   347.5 1571.46   357.4 1576.82
   367.4 1581.65   387.2 1589.72   407.1 1596.68   466.6 1615.94   536.1 1640.29
   565.9 1650.11   595.7 1659.24   625.5 1668.00   645.4 1673.41   685.1 1683.57
#Mann= 3 , 0 , 0
       0     0.1       0   144.6   0.045       0   156.6     0.1       0
Bank Sta=   144.6,   156.6
Exp/Cntr=0.3,0.1

Type RM Length L Ch R = 1 ,819.4,279,271.3,263.7
XS GIS Cut Line= 2
     1934435.368      336705.262     1935159.240      336936.541
#Sta/Elev= 30
       0 1565.76    30.0 1545.45    70.0 1524.17    90.0 1514.10   120.0 1500.19
   160.0 1482.86   220.0 1458.25   226.9 1456.20   230.0 1455.28   238.9 1454.52
   260.0 1453.88   270.0 1454.22   280.0 1456.14   290.0 1459.50   310.0 1468.01
   320.0 1472.90   340.0 1483.93   400.0 1522.03   420.0 1533.60   450.0 1547.97
   510.0 1577.85   539.9 1591.42   559.9 1599.20   579.9 1606.16   589.9 1609.06
   599.9 1611.15   619.9 1613.80   679.9 1624.54   729.9 1631.95   759.9 1638.75
#Mann= 3 , 0 , 0
       0     0.1       0   226.9   0.045       0   238.9     0.1       0
Bank Sta=   226.9,   238.9
Exp/Cntr=0.3,0.1

Type RM Length L Ch R = 1 ,548.1,356.4,356.3,356.2
XS GIS Cut Line= 2
     1934034.844      337058.838     1935143.544      337000.340
#Sta/Elev= 30
       0 1606.06    60.0 1612.91   130.0 1626.44   140.0 1626.84   150.0 1624.82
   170.0 1614.74   180.0 1611.42   200.0 1606.85   210.0 1602.92   240.0 1589.21
   270.1 1573.71   360.1 1521.92   410.1 1495.05   440.1 1480.16   480.1 1461.71
   510.1 1448.44   520.1 1444.55     526 1443.64   530.1 1443.00     538 1443.07
   580.1 1446.98   590.1 1450.02   790.2 1536.51   900.2 1593.51   950.2 1618.70
   960.2 1623.04  1010.2 1638.94  1080.2 1665.51  1090.2 1668.25  1110.2 1671.71
#Mann= 3 , 0 , 0
       0     0.1       0     526   0.045       0     538     0.1       0
Bank Sta=     526,     538
Exp/Cntr=0.3,0.1

Type RM Length L Ch R = 1 ,191.8,52.5,53.2,53.8
XS GIS Cut Line= 2
     1934519.077      337375.660     1934790.663      337359.416
#Sta/Elev= 21
       0 1450.42     9.7 1445.18    19.4 1442.39    29.2 1441.51    58.3 1440.14
    77.7 1438.90   116.6 1436.13   126.3 1435.36   145.8 1433.65   148.1 1433.54
   155.5 1433.18   160.1 1433.49   165.2 1433.84   194.3 1439.15   204.0 1441.95
   213.8 1446.03   223.5 1450.74   233.2 1455.58   252.6 1465.50   262.4 1470.58
   272.1 1475.76
#Mann= 3 , 0 , 0
       0     0.1       0   148.1   0.045       0   160.1     0.1       0
Bank Sta=   148.1,   160.1
Exp/Cntr=0.3,0.1

Type RM Length L Ch R = 1 ,138.6,143.1,138.6,134.2
XS GIS Cut Line= 2
     1934501.073      337423.331     1934866.212      337411.198
#Sta/Elev= 25
       0 1440.52    29.6 1439.84    49.4 1439.58    59.2 1439.36    69.1 1439.02
    79.0 1438.56    88.9 1438.00   108.6 1436.57   158.0 1432.17   167.9 1431.49
   177.7 1430.98   182.2 1430.87   187.6 1430.73   194.2 1431.00   197.5 1431.14
   217.2 1433.33   237.0 1435.19   246.8 1436.34   256.7 1438.47   266.6 1442.20
   276.5 1447.14   286.4 1452.45   316.0 1468.56   355.5 1490.85   365.3 1496.46
#Mann= 3 , 0 , 0
       0     0.1       0   182.2   0.045       0   194.2     0.1       0
Bank Sta=   182.2,   194.2
Exp/Cntr=0.3,0.1